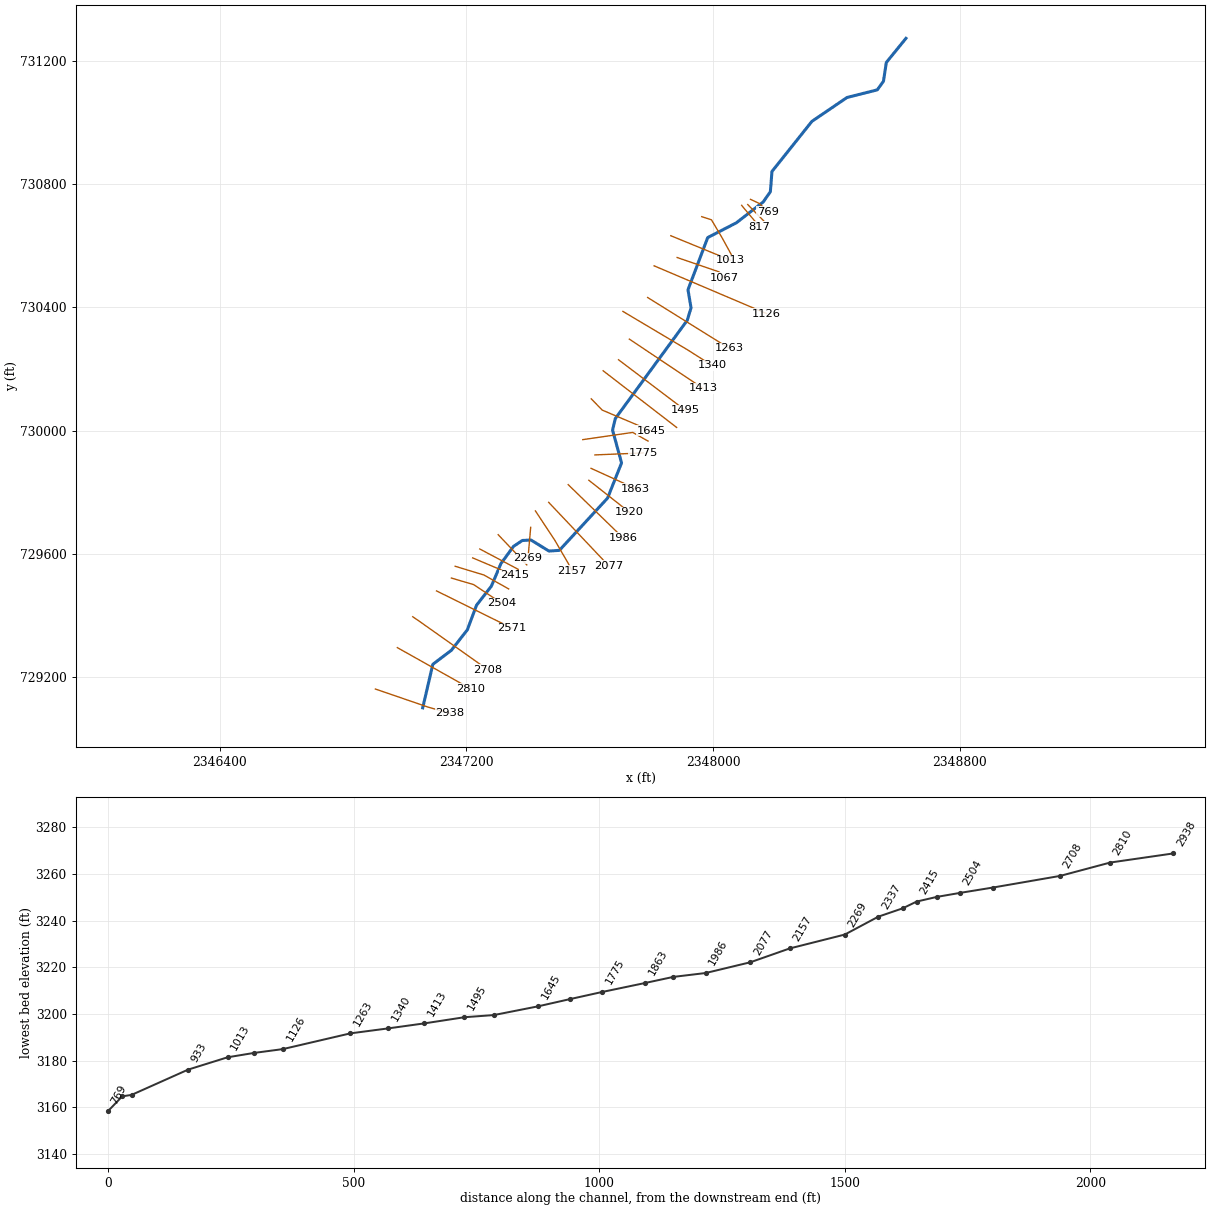
--- MOORERNT1.prj (project) ---

Proj Title=MOORERNT1
Current Plan=p01
Default Exp/Contr=0,0
English Units
Geom File=g01
Flow File=f01
Plan File=p01
BEGIN DESCRIPTION:
----------MODEL BY WOOD PLC 2022----------
AFH study
Randolph County, WV
HEC-RAS Version: RAS 6.2
Vertical Datum: NAVD88
Projection: NAD 1983 StatePlane West Virginia S FIPS 4702 (US Feet)
Terrain: 1-meter LIDAR (FEMA Region III 3DEP collected 2016-2018)
Land Use: 2019 NLCD
Hydrologic Method:
WV SIR2010-5033 regression equations
Additional Model Notes:
None
END DESCRIPTION:
DSS Export Rating Curves= 0
DSS Export Rating Curve Sorted= 0
DSS Export Volume Flow Curves= 0
DXF OffsetX= 0
DXF OffsetY= 0
DXF ScaleX= 0
DXF ScaleY= 0

--- MOORERNT1.p01 (plan) ---

Plan Title=Floodplain
Program Version=6.20
Short Identifier=Floodplain
Geom File=g01
Flow File=f01
Subcritical Flow
K Sum by GR= 0
Std Step Tol= 0.01
Critical Tol= 0.01
Num of Std Step Trials= 20
Max Error Tol= 0.3
Flow Tol Ratio= 0.001
Split Flow NTrial= 30
Split Flow Tol= 0.02
Split Flow Ratio= 0.02
Log Output Level= 0
Friction Slope Method= 1
Unsteady Friction Slope Method= 2
Unsteady Bridges Friction Slope Method= 1
Parabolic Critical Depth
Global Vel Dist= 0 , 0 , 0
Global Log Level= 0
CheckData=True
Encroach Param=-1 ,0,0, 0
Mapping Interval=1HOUR
Computation Time Step Use Courant=        0
Computation Time Step Use Time Series=    0
Computation Time Step Count To Double=0
Computation Time Step Max Doubling=0
Computation Time Step Max Halving=0
Computation Time Step Residence Courant=0
Run HTab= 0
Run UNet= 0
Run Sediment= 0
Run PostProcess= 0
Run WQNet= 0
Run RASMapper=-1
UNET Theta= 0
UNET Theta Warmup= 0
UNET ZTol= 0
UNET ZSATol= 0
UNET MxIter= 0
UNET Max Iter WO Improvement= 0
UNET MaxInSteps= 0
UNET DtIC= 0
UNET DtMin= 0
UNET MaxCRTS= 0
UNET WFStab= 0
UNET SFStab= 0
UNET WFX= 1
UNET SFX= 1
UNET Gravity=32.174
UNET 1D Methodology=Finite Difference
UNET DSS MLevel= 1
UNET Pardiso=0
UNET DZMax Abort= 0
UNET Use Existing IB Tables= 0
UNET Froude Reduction=False
UNET Froude Limit= 0
UNET Froude Power= 0
UNET D1 Cores= 0
UNET WindReference=Eulerian
UNET WindDragFormulation=Hsu (1988)
UNET D2 Coriolis=0
UNET D2 Cores= 0
UNET D2 Theta= 1
UNET D2 Theta Warmup= 1
UNET D2 Z Tol= 0.01
UNET D2 Volume Tol= 0.01
UNET D2 Max Iterations= 20
UNET D2 Equation= 0
UNET D2 RampUpFraction=0.1
UNET D2 TimeSlices= 1
UNET D2 Turbulence Formulation=Non-Conservative (original)
UNET D2 Eddy Viscosity=0.3
UNET D2 Transverse Eddy Viscosity=0.1
UNET D2 Smagorinsky Mixing=0
UNET D2 BCVolumeCheck=0
UNET D2 Cores=0
UNET D2 SolverType=PARDISO (Direct)
UNET D2 Minimum Iterations= 2147483647
UNET D2 Maximum Iterations= 2147483647
UNET D2 Restart Number= 10
UNET D2 Relaxation Coeff=1.3
UNET D2 SOR Precondition Iterations= 10
UNET D2 ILUT Maximum Fill= 8
UNET D2 ILUT Tolerance=1E-08
UNET D1D2 MaxIter= 0
UNET D1D2 ZTol=0.01
UNET D1D2 QTol=0.1
UNET D1D2 MinQTol=1
Write IC File= 0
Write IC File at Fixed DateTime=0
Write IC File at Sim End=0
Echo Input=False
Echo Parameters=False
Echo Output=False
Write Detailed= 0
HDF Write Warmup=0
HDF Write Time Slices=0
HDF Flush=0
HDF Compression= 1
HDF Chunk Size= 1
HDF Spatial Parts= 1
HDF Use Max Rows=0
HDF Fixed Rows= 1
Calibration Method= 0
Calibration Iterations= 20
Calibration Max Change=0.05
Calibration Tolerance=0.2
Calibration Maximum=1.5
Calibration Minimum=0.5
Calibration Optimization Method= 1
WQ AD Non Conservative
WQ ULTIMATE=-1
WQ Max Comp Step=1HOUR
WQ Output Interval=15MIN
WQ Output Selected Increments= 0
WQ Output face flow=0
WQ Output face velocity=0
WQ Output face area=0
WQ Output face dispersion=0
WQ Output cell volume=0
WQ Output cell surface area=0
WQ Output cell continuity=0
WQ Output cumulative cell continuity=0
WQ Output face conc=0
WQ Output face dconc_dx=0
WQ Output face courant=0
WQ Output face peclet=0
WQ Output face adv mass=0
WQ Output face disp mass=0
WQ Output cell mass=0
WQ Output cell source sink temp=0
WQ Output nsm pathways=0
WQ Output nsm derived pathways=0
WQ Create Restart=0
WQ Fixed Restart=0
WQ System Summary=0
WQ Write To DSS=0
Sorting and Armoring Iterations= 10
XS Update Threshold= 0.02
Bed Roughness Predictor= 0
Hydraulics Update Threshold= 0.02
Energy Slope Method= 1
Volume Change Method= 1
Sediment Retention Method= 0
Sediment TS Multiplier= 1
Warm Up Method= 0
XS Weighting Method= 0
Number of US Weighted Cross Sections= 1
Number of DS Weighted Cross Sections= 1
Upstream XS Weight=0
Main XS Weight=1
Downstream XS Weight=0
Number of DS XS's Weighted with US Boundary= 1
Upstream Boundary Weight= 1
Weight of XSs Associated with US Boundary= 0
Number of US XS's Weighted with DS Boundary= 1
Downstream Boundary Weight= 0.5
Weight of XSs Associated with DS Boundary= 0.5
Percentile Method= 0
Sediment Output Level= 3
Mass or Volume Output= 0
Output Increment Type= 1
Profile and TS Output Increment= 1
Transport Output Increment 1
XS Output Flag= 0
XS Output Increment= 10
Read HDF5 Sediment Hotstart= 0
Sediment Hotstart Type= 0
Write Gradation File= 0
Read Gradation Hotstart= 0
Write HDF5 File= 1
Write Binary Output= 1
Write DSS Sediment File= 0
DSS Sediment Output Type= 1
SV Curve= 0
Specific Gage Flag= 0
Subcell Erosion Methods= 0
Subcell Deposition Methods= 0
Advection Scheme= 1
Matrix Solver= 0
Implicit Weighting Factor= 1
Maximum Outer Loop Convergence Iterations= 5
Convergence Maximum Absolute= 0.001
Convergence RMSE= 0.0001
Grain Fractions Max Abs Error= 0.001
Max Subgrid Regions= 1
Max Subgrid Length Scale= 3.402823E+38
Initial Layer Thickness= 3.402823E+38
Min Layer Thickness= 3.402823E+38
Max Layer Thickness= 3.402823E+38
Number of Layers= 5

--- MOORERNT1.f01 (steady flow) ---

Flow Title=Flow
Program Version=6.20
Number of Profiles= 1
Profile Names=P100yr
River Rch & RM=MOORERNT1,Main,2938
     356
Boundary for River Rch & Prof#=MOORERNT1,Main            , 1
Up Type= 0
Dn Type= 3
Dn Slope=0.04101
DSS Import GetInterval= 0
DSS Import GetPeak= 0
DSS Import FillOption= 0

--- MOORERNT1.g01 (geometry) ---

Geom Title=Geometry
Program Version=6.20

River Reach=MOORERNT1       ,Main
Reach XY= 30
2347058.79099999729101.1480000022347091.60400003729242.295000017
2347151.71200001729287.8400000042347203.58300002729354.274000019
2347233.27100003729433.9609999952347281.18700004729495.419000015
2347312.43700002729568.8569999932347353.06200004729624.585999995
2347381.70800003729643.856999993     2347409.833729645.419000015
2347468.16700001729609.482000008      2347501.95729611.851999998
2347658.27000003729781.3569999932347703.58300002729895.420000017
2347674.41600004      730001.6692347683.27099998730039.170000017
2347916.60400003730357.9200000172347928.92900001730398.186000004
2347919.00600003730456.8660000122347983.00100002730626.112000003
2348075.79300001730673.9300000222348162.84200002730741.483999997
2348186.10600004730774.818000019     2348191.315730840.443000019
2348320.82900003731002.9430000192348434.71700002731080.373000011
2348532.63400002731105.0259999932348552.77300002731132.804000005
2348562.14800003731193.915000021 2348625.8089357731272.172915738

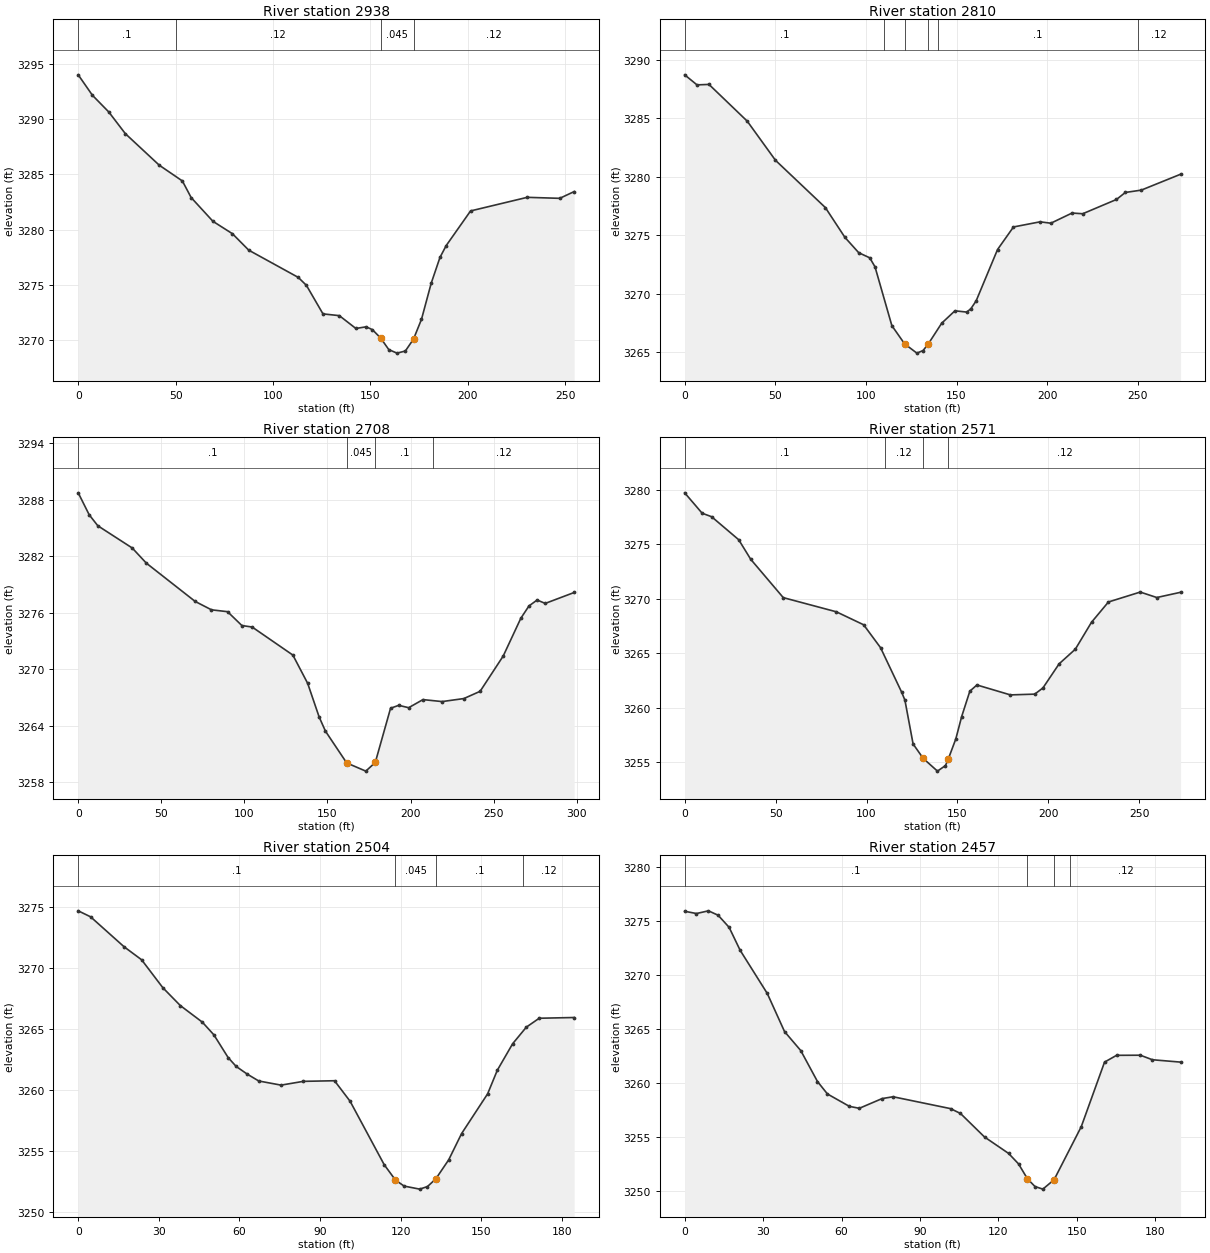
Type RM Length L Ch R = 1 ,2938    ,129.2,128.6,127.4
XS GIS Cut Line= 3
2346905.28605991729162.1950712932347076.78044155729103.395290154
2347147.34513012729083.233950564
#Sta/Elev= 30
       0 3293.99     7.3 3292.14    15.7 3290.63    24.2 3288.67    41.6 3285.82
    53.5 3284.39      58 3282.89    69.2 3280.74    79.2 3279.62    87.6 3278.13
     113 3275.67   117.2 3274.95   125.7 3272.37   134.1 3272.21   142.6 3271.05
   147.9  3271.2   151.1 3270.94   155.3 3270.19   159.5 3269.14   163.7 3268.82
     168 3269.01   172.2 3270.09   176.3 3271.88   181.3 3275.15   185.8 3277.48
     189 3278.55   201.5 3281.68   230.6 3282.91   247.3 3282.82   254.7 3283.43
#Mann= 4 ,-1,0
       0      .1       0      50     .12       0   155.3    .045       0
   172.2     .12       0
Bank Sta=155.3,172.2
XS Rating Curve= 0 ,0
Exp/Cntr(USF)=0,0
Exp/Cntr=0.3,0.1

Type RM Length L Ch R = 1 ,2810    ,102.5,102,102.3
XS GIS Cut Line= 2
2346976.49640028729296.4853535612347215.03076786729162.525835535
#Sta/Elev= 30
       0 3288.71     6.8 3287.85    13.4 3287.89    34.5 3284.75    50.1  3281.4
    77.6 3277.36    88.4 3274.81      96  3273.5   102.1 3273.06     105 3272.29
   114.3 3267.26  121.34  3265.7   128.1 3264.91   131.5 3265.13   134.33265.675
   141.8 3267.47   149.1 3268.53   155.6 3268.42   157.9 3268.71   160.8 3269.38
   172.6 3273.77   181.4  3275.7   196.1 3276.14     202 3276.02   213.7 3276.89
   219.6 3276.83   238.2 3278.05   243.1 3278.65   251.9 3278.85   273.6 3280.21
#Mann= 6 ,-1,0
       0      .1       0     110     .12       0  121.34    .045       0
   134.3     .12       0     140      .1       0     250     .12       0
Bank Sta=121.34,134.3
XS Rating Curve= 0 ,0
Exp/Cntr(USF)=0,0
Exp/Cntr=0.3,0.1

Type RM Length L Ch R = 1 ,2708    ,136,136.9,138.6
XS GIS Cut Line= 3
2347026.43067823729396.5794571072347046.03198061 729383.27857335
2347270.34935418729224.497653017
#Sta/Elev= 30
       0 3288.75     6.6 3286.42    11.8 3285.25    32.5 3282.89      41 3281.28
    70.4 3277.21    80.2 3276.32    89.9 3276.12    98.5 3274.65   104.7 3274.49
   129.2 3271.51   138.1 3268.51     145 3264.94   148.8 3263.43   161.6 3260.05
   173.1 3259.18   178.8  3260.1     188 3265.86   192.9 3266.17   198.9 3265.92
   207.5 3266.78     219 3266.57   232.1 3266.89   241.9 3267.66   255.8 3271.41
   266.4 3275.42   271.3 3276.73   276.2 3277.36   281.1    3277   298.5 3278.16
#Mann= 4 ,-1,0
       0      .1       0   161.6    .045       0   178.8      .1       0
  213.69     .12       0
Bank Sta=161.6,178.8
XS Rating Curve= 0 ,0
Exp/Cntr(USF)=0,0
Exp/Cntr=0.3,0.1

Type RM Length L Ch R = 1 ,2571    ,67.4,66.6,65.7
XS GIS Cut Line= 2
2347103.58677259729480.3500894232347348.12603093729359.575965276
#Sta/Elev= 30
       0 3279.71     9.6 3277.84    14.8 3277.52    29.7 3275.41    36.3 3273.62
    54.2  3270.1    83.4  3268.8    98.4 3267.61   107.7 3265.51   119.3 3261.43
   121.1  3260.7   125.6 3256.68   131.2 3255.35     139 3254.19   143.4  3254.7
  145.02 3255.33   149.1 3257.15   152.3 3259.19   156.8 3261.52   160.7 3262.09
   179.1 3261.18   192.5 3261.25     197 3261.82   205.9 3264.03   214.8 3265.37
   223.7 3267.84     233  3269.7   250.5 3270.61   259.6 3270.11   272.7 3270.59
#Mann= 4 ,-1,0
       0      .1       0     110     .12       0   131.2    .045       0
  145.02     .12       0
Bank Sta=131.2,145.02
XS Rating Curve= 0 ,0
Exp/Cntr(USF)=0,0
Exp/Cntr=0.3,0.1

Type RM Length L Ch R = 1 ,2504    ,46.9,47.3,47.8
XS GIS Cut Line= 3
 2347151.7535151729522.0849141772347224.20383956729500.726105238
2347315.05938572729440.326061831
#Sta/Elev= 30
       0 3274.71     4.6 3274.22    17.1 3271.76    23.6  3270.7    31.5 3268.41
      38 3266.95    46.2 3265.59    50.5 3264.55    55.8 3262.69    58.8 3261.96
      63 3261.32    67.2 3260.77    75.5 3260.43    83.8 3260.74    95.4 3260.79
   101.2 3259.11   113.9 3253.91   118.1 3252.65   121.3 3252.16   127.1 3251.91
     130 3252.12   133.1 3252.75   137.9 3254.31   142.7 3256.46   152.4 3259.72
     156 3261.65   161.7 3263.82   166.8 3265.18   171.6 3265.91   184.6 3265.97
#Mann= 4 ,-1,0
       0      .1       0   118.1    .045       0   133.1      .1       0
  165.53     .12       0
Bank Sta=118.1,133.1
XS Rating Curve= 0 ,0
Exp/Cntr(USF)=0,0
Exp/Cntr=0.3,0.1

Type RM Length L Ch R = 1 ,2457    ,41.4,41.3,41.9
XS GIS Cut Line= 3
2347163.90530323 729560.275461622347257.19728846 729531.96857723
2347337.55650701729486.766516796
#Sta/Elev= 30
       0 3275.94     4.5 3275.73     9.1 3275.98    12.8 3275.57      17 3274.45
    21.2 3272.33    31.6 3268.32    38.2 3264.79    44.4 3263.03    50.8 3260.16
    54.6 3259.01      63 3257.86    66.8 3257.68    75.5 3258.58    79.7 3258.75
   101.7 3257.65   105.5  3257.2   114.7 3255.02   123.9  3253.5   127.7 3252.53
   131.1 3251.15     134 3250.43     137 3250.19   141.3 3251.06   151.7 3255.98
   160.6 3261.96   165.2 3262.59   174.3  3262.6   178.9 3262.18   189.7 3261.96
#Mann= 4 ,-1,0
       0      .1       0   131.1    .045       0   141.3      .1       0
  147.49     .12       0
Bank Sta=131.1,141.3
XS Rating Curve= 0 ,0
Exp/Cntr(USF)=0,0
Exp/Cntr=0.3,0.1

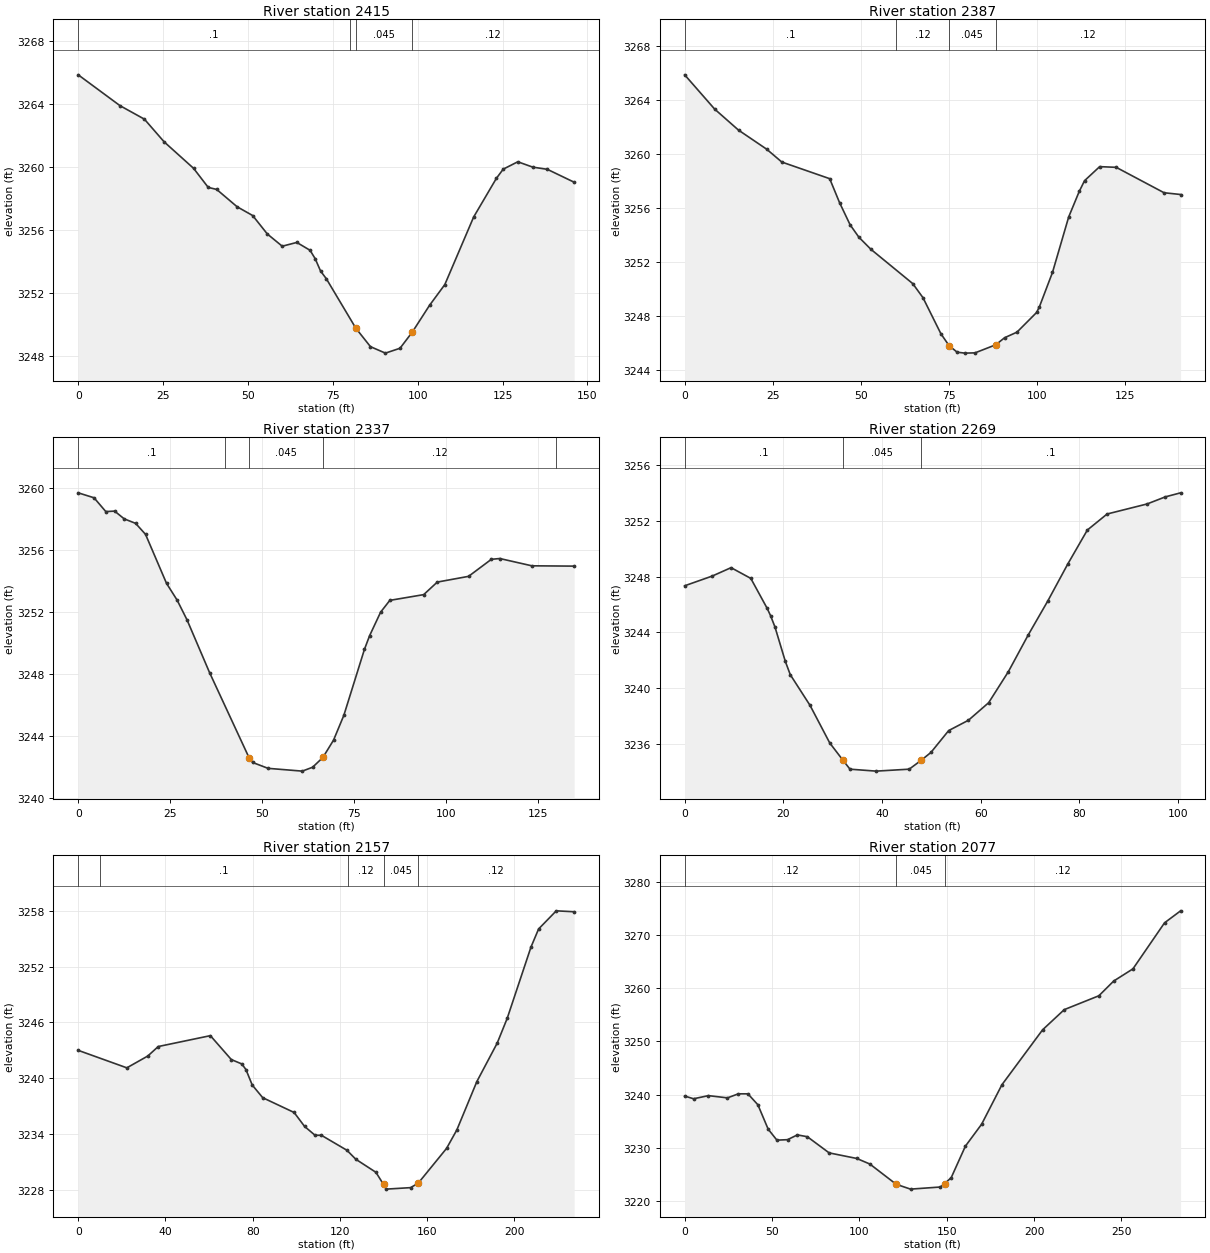
Type RM Length L Ch R = 1 ,2415    ,29.3,28.5,28
XS GIS Cut Line= 2
2347220.87292509729587.4142967712347355.44797673729530.461032596
#Sta/Elev= 30
       0 3265.88    12.3 3263.92    19.5 3263.06    25.3 3261.62      34 3259.93
    38.3 3258.72    40.8 3258.59    46.8 3257.49    51.4 3256.93    55.7 3255.76
    60.1 3254.98    64.4 3255.22    68.3 3254.72    69.8 3254.19    71.4  3253.4
    73.1 3252.91    81.8 3249.76    86.1 3248.59    90.5 3248.18    94.8 3248.49
    98.43249.511   103.5 3251.22     108 3252.54   116.5 3256.84   123.2  3259.3
   125.2 3259.88   129.5 3260.35   133.9 3260.01   138.2 3259.87   146.1 3259.05
#Mann= 4 ,-1,0
       0      .1       0      80     .12       0    81.8    .045       0
    98.4     .12       0
Bank Sta=81.8,98.4
XS Rating Curve= 0 ,0
Exp/Cntr(USF)=0,0
Exp/Cntr=0.3,0.1

Type RM Length L Ch R = 1 ,2387    ,54.1,49.5,48.1
XS GIS Cut Line= 2
2347243.80408537729616.3457567072347368.36087412729550.384231481
#Sta/Elev= 30
       0 3265.86     8.5 3263.33    15.3 3261.77    23.3 3260.36    27.6 3259.41
    41.2 3258.18      44 3256.41      47 3254.77    49.5 3253.85    52.9 3252.96
    64.8 3250.42    67.7 3249.38    72.8 3246.71    75.1 3245.84    77.4 3245.35
    79.6 3245.28    82.5  3245.3    88.4  3245.9    90.9 3246.42    94.4 3246.83
     100 3248.29   100.8 3248.72   104.5 3251.25   109.1 3255.35   112.1 3257.24
   113.6 3258.03   117.9 3259.07   122.6 3259.02   136.2 3257.14   140.9 3257.01
#Mann= 4 ,-1,0
       0      .1       0      60     .12       0    75.1    .045       0
    88.4     .12       0
Bank Sta=75.1,88.4
XS Rating Curve= 0 ,0
Exp/Cntr(USF)=0,0
Exp/Cntr=0.3,0.1

Type RM Length L Ch R = 1 ,2337    ,78.2,68.3,63.4
XS GIS Cut Line= 2
2347303.57687278729662.6275123222347396.35557732729564.796502085
#Sta/Elev= 30
       0 3259.67     4.3 3259.35     7.5 3258.46     9.9 3258.49    12.5 3257.99
    15.6  3257.7    18.3 3256.99      24 3253.83    26.9 3252.74    29.6 3251.46
    35.7 3248.07   46.43 3242.58    47.4 3242.27    51.6 3241.89    60.9 3241.71
    63.7 3241.96    66.5 3242.59    69.4 3243.71    72.2 3245.31    77.8 3249.57
    79.2 3250.45    82.2 3251.97    84.7 3252.73    93.9  3253.1    97.6 3253.91
   106.1 3254.28   112.3 3255.38   114.6 3255.43   123.3 3254.96   134.8 3254.94
#Mann= 5 ,-1,0
       0      .1       0      40     .12       0   46.43    .045       0
    66.5     .12       0     130      .1       0
Bank Sta=46.43,66.5
XS Rating Curve= 0 ,0
Exp/Cntr(USF)=0,0
Exp/Cntr=0.3,0.1

Type RM Length L Ch R = 1 ,2269    ,105.2,112.3,115.3
XS GIS Cut Line= 2
 2347408.8987378729686.5057479642347400.19315579729586.391554855
#Sta/Elev= 29
       0 3247.34     5.6 3248.04     9.4 3248.64    13.4 3247.87    16.7 3245.73
    17.4  3245.2    18.3 3244.38    20.4 3241.91    21.4 3240.96    25.4 3238.76
    29.4 3236.06    32.1 3234.81    33.5 3234.18    38.8 3234.04    45.5 3234.18
    47.9 3234.81    49.9 3235.38    53.5 3236.95    57.5 3237.69    61.6 3238.95
    65.6 3241.18    69.6  3243.8    73.6 3246.26    77.6 3248.88    81.6 3251.34
    85.6 3252.49    93.7 3253.21    97.4 3253.72   100.5 3254.01
#Mann= 3 ,0,0
       0      .1       0    32.1    .045       0    47.9      .1       0
Bank Sta=32.1,47.9
XS Rating Curve= 0 ,0
Exp/Cntr(USF)=0,0
Exp/Cntr=0.3,0.1

Type RM Length L Ch R = 1 ,2157    ,77.4,79.9,80.7
XS GIS Cut Line= 4
2347424.24287236729739.7647282432347486.90212351729644.993576564
2347530.71994707729569.6534254482347542.76583529729545.866990246
#Sta/Elev= 30
       0    3243    22.3 3241.12    31.9 3242.39    36.7 3243.41    60.6 3244.58
    70.2 3242.01      75 3241.54    76.9 3240.94    79.8 3239.27    84.6 3237.91
      99 3236.32   103.8 3234.82   108.6 3233.87   111.5 3233.87   123.2 3232.26
   127.3 3231.29   136.5 3229.89     140 3228.58   141.2 3228.08   152.4 3228.24
   155.9 3228.72   168.9 3232.46   173.6 3234.44   182.8 3239.65   192.1 3243.77
   196.7 3246.44   207.6  3254.1   211.1 3256.05   219.2    3258   227.4  3257.9
#Mann= 5 ,-1,0
       0     .12       0      10      .1       0  123.61     .12       0
     140    .045       0   155.9     .12       0
Bank Sta=140,155.9
XS Rating Curve= 0 ,0
Exp/Cntr(USF)=0,0
Exp/Cntr=0.3,0.1

Type RM Length L Ch R = 1 ,2077    ,90.6,91,92.5
XS GIS Cut Line= 2
2347467.30082113729767.5017164362347662.49242401729561.307993018
#Sta/Elev= 30
       0 3239.71     5.1  3239.2    13.6 3239.79    24.5 3239.37    30.7 3240.13
    36.2 3240.13    41.9 3238.07    47.8 3233.47    52.8  3231.4    58.9 3231.49
    64.5 3232.39    70.2 3232.05    82.7    3229    98.5 3227.95     106  3226.9
   121.1 3223.08   129.3 3222.17   146.4 3222.57   148.93223.222   152.6 3224.35
   160.7 3230.27     170 3234.41   181.6 3241.84   204.9  3252.2   217.3    3256
   237.1 3258.61   245.6 3261.39   256.6 3263.68   274.7 3272.36   283.9 3274.62
#Mann= 3 ,-1,0
       0     .12       0   121.1    .045       0   148.9     .12       0
Bank Sta=121.1,148.9
XS Rating Curve= 0 ,0
Exp/Cntr(USF)=0,0
Exp/Cntr=0.3,0.1

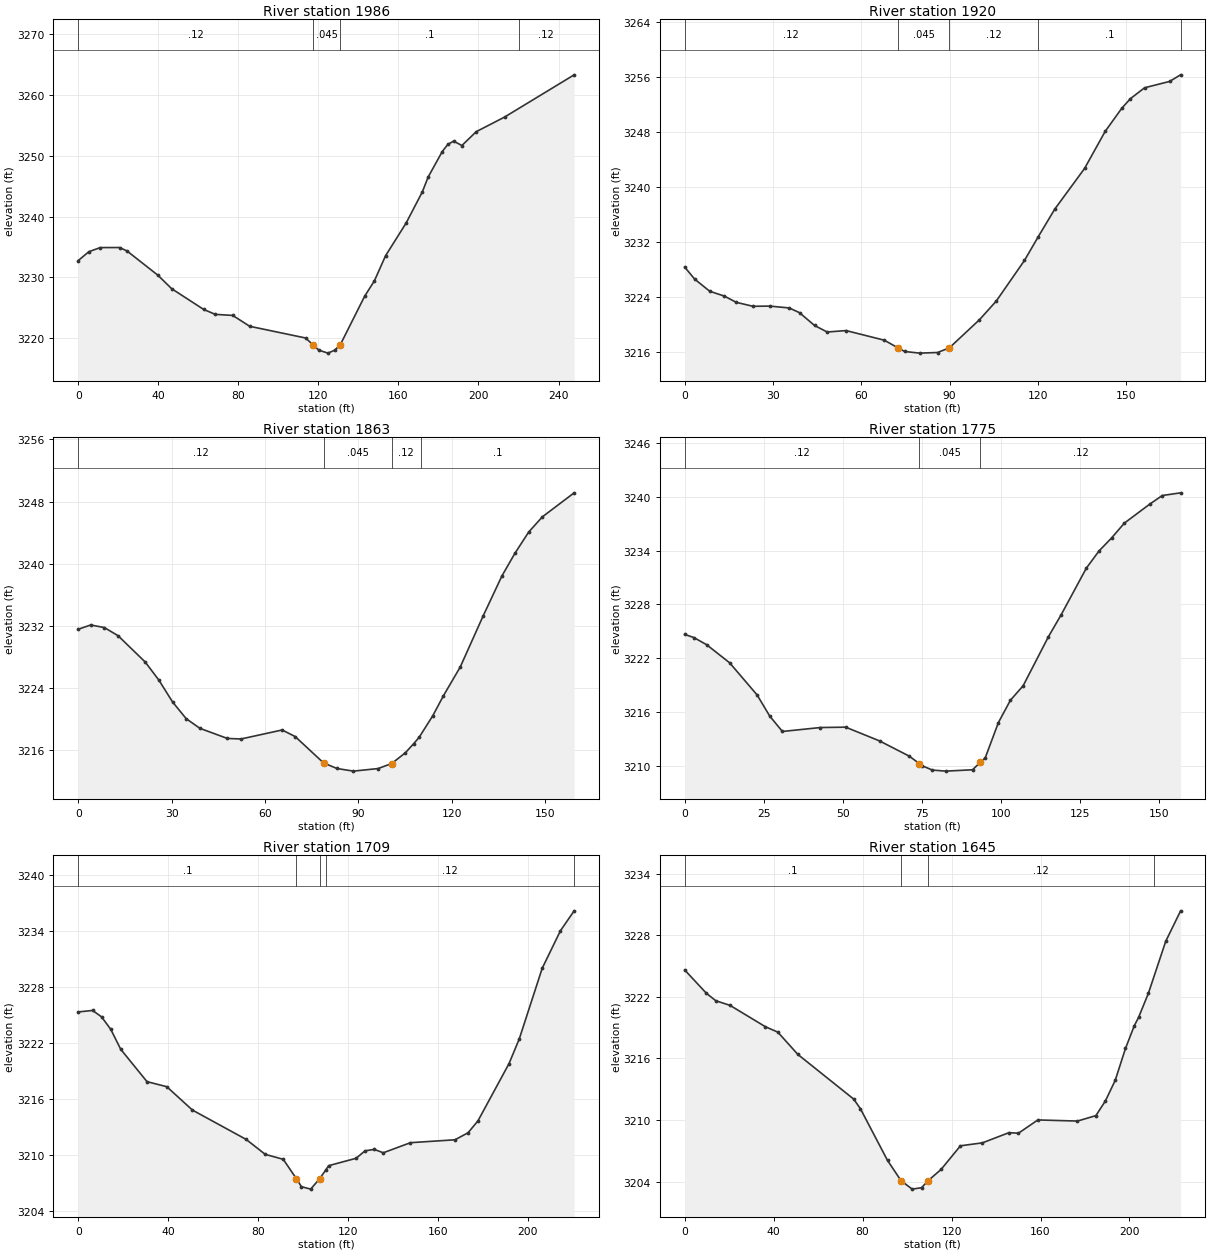
Type RM Length L Ch R = 1 ,1986    ,64.9,65.7,66.3
XS GIS Cut Line= 2
2347530.63347033729824.8675960642347708.46370799729652.306402488
#Sta/Elev= 30
       0 3232.77     5.3 3234.23      11 3234.91    20.7 3234.92    24.4 3234.35
    39.8 3230.37    46.7 3228.15    62.7 3224.74    68.5 3223.93    77.2 3223.76
    85.7 3221.97   113.6 3220.05  117.23 3218.96   120.2 3218.05   124.8 3217.56
   128.2 3218.05     131 3218.97   143.1  3226.9     148 3229.45   153.6 3233.59
   163.8 3238.92   171.9 3244.04   174.9 3246.54   181.9  3250.7   184.7 3251.88
   187.6 3252.41   191.7 3251.69   198.9 3253.97     213 3256.36   247.8 3263.31
#Mann= 4 ,-1,0
       0     .12       0  117.23    .045       0     131      .1       0
     220     .12       0
Bank Sta=117.23,131
XS Rating Curve= 0 ,0
Exp/Cntr(USF)=0,0
Exp/Cntr=0.3,0.1

Type RM Length L Ch R = 1 ,1920    ,55.4,57.7,59.6
XS GIS Cut Line= 2
2347597.53353241729839.1274742612347729.81208146729734.866256778
#Sta/Elev= 30
       0 3228.42     3.4 3226.66     8.5  3224.9    13.5 3224.19    17.5 3223.29
    23.2 3222.71    28.9 3222.74    35.5 3222.47      39 3221.78    44.1 3219.92
    48.4 3218.97    54.8 3219.18    67.8 3217.78   72.38 3216.68    74.7 3216.14
    79.8  3215.9    85.9 3215.99    89.9 3216.67   100.1 3220.75   105.8 3223.46
   115.4 3229.38     120 3232.77   125.7 3236.85   135.8 3242.75   142.8 3248.14
   148.5 3251.54   151.4 3252.91   156.2 3254.49   164.7 3255.41   168.4 3256.37
#Mann= 5 ,-1,0
       0     .12       0   72.38    .045       0    89.9     .12       0
     120      .1       0  168.43     .12       0
Bank Sta=72.38,89.9
XS Rating Curve= 0 ,0
Exp/Cntr(USF)=0,0
Exp/Cntr=0.3,0.1

Type RM Length L Ch R = 1 ,1863    ,81.8,87.8,91.6
XS GIS Cut Line= 2
2347604.57123419729877.8883391372347749.48086249729811.733943606
#Sta/Elev= 30
       0 3231.55       4  3232.1     8.4 3231.77    12.8 3230.72    21.5 3227.34
    25.9 3225.01    30.3 3222.19    34.7 3220.03    39.1 3218.79    47.9 3217.49
    52.3 3217.42    65.5 3218.58    69.7 3217.73    78.8 3214.34    83.1 3213.62
    88.4 3213.28    96.3 3213.61   100.7 3214.26   105.1 3215.65   107.7 3216.79
   109.5 3217.63   113.9 3220.42   117.3 3222.98   122.7 3226.68     130 3233.21
   136.1 3238.42   140.3 3241.35   144.7 3244.07   149.1 3246.03   159.3 3249.12
#Mann= 4 ,-1,0
       0     .12       0    78.8    .045       0   100.7     .12       0
     110      .1       0
Bank Sta=78.8,100.7
XS Rating Curve= 0 ,0
Exp/Cntr=0.3,0.1

Type RM Length L Ch R = 1 ,1775    ,63.1,65.8,67
XS GIS Cut Line= 2
2347617.28345466729921.3422669022347773.90493115729927.772474148
#Sta/Elev= 30
       0 3224.65     2.9  3224.3     6.9 3223.51    14.2 3221.49    22.9  3217.9
    26.9 3215.54    30.9 3213.83    42.9 3214.27    50.9 3214.31    61.6 3212.78
      71 3211.08    74.2 3210.25      75 3210.02    78.3 3209.53    82.5 3209.41
      91 3209.56    93.5  3210.4      95 3210.87    99.2 3214.83     103 3217.32
     107 3218.92     115 3224.39     119 3226.82     127 3232.04     131 3233.95
     135 3235.41     139 3237.05     147 3239.16     151 3240.13   156.8 3240.43
#Mann= 3 ,-1,0
       0     .12       0    74.2    .045       0    93.5     .12       0
Bank Sta=74.2,93.5
XS Rating Curve= 0 ,0
Exp/Cntr(USF)=0,0
Exp/Cntr=0.3,0.1

Type RM Length L Ch R = 1 ,1709    ,66.7,64.4,60.7
XS GIS Cut Line= 3
2347577.86832971729970.9182398172347739.65685728729994.253123602
2347789.43794269 729966.25126306
#Sta/Elev= 30
       0  3225.3     6.4 3225.46    10.4 3224.77    14.5 3223.43    18.9 3221.31
    30.6 3217.84    39.4  3217.3    50.8  3214.8    74.7 3211.66    83.2 3210.06
    91.2 3209.53   97.07 3207.45    99.3  3206.6   103.4 3206.34   107.4 3207.46
     110 3208.35   111.4 3208.85   123.6 3209.64   127.6 3210.44   131.7 3210.59
   135.7 3210.23   147.8 3211.31   167.6 3211.62   173.4 3212.37   177.8 3213.64
   191.6 3219.76   196.2 3222.42   206.4 3229.98   214.5 3233.99   220.6 3236.12
#Mann= 5 ,-1,0
       0      .1       0   97.07    .045       0   107.4      .1       0
     110     .12       0  220.58      .1       0
Bank Sta=97.07,107.4
XS Rating Curve= 0 ,0
Exp/Cntr(USF)=0,0
Exp/Cntr=0.3,0.1

Type RM Length L Ch R = 1 ,1645    ,91.1,89.8,88.1
XS GIS Cut Line= 3
 2347605.3515715730103.1939934072347640.88205298 730066.70322864
2347799.32879473729999.483398806
#Sta/Elev= 30
       0 3224.62     9.8 3222.34      14 3221.62    20.4 3221.17    36.3 3219.09
    41.9 3218.56    50.9 3216.39      76 3212.04      79 3211.11    91.2 3206.07
    97.3 3204.09   102.3 3203.27   106.5 3203.41   109.5  3204.1   115.3 3205.19
     124 3207.49   133.9 3207.78   145.8 3208.77   150.1 3208.72   158.8 3210.01
   176.6  3209.9   184.9 3210.43   189.2 3211.87   193.6 3213.87   198.2 3216.97
   202.2  3219.2   204.1    3220   208.5 3222.34   216.3 3227.41     223 3230.38
#Mann= 4 ,-1,0
       0      .1       0    97.3    .045       0   109.5     .12       0
  210.93      .1       0
Bank Sta=97.3,109.5
XS Rating Curve= 0 ,0
Exp/Cntr(USF)=0,0
Exp/Cntr=0.3,0.1

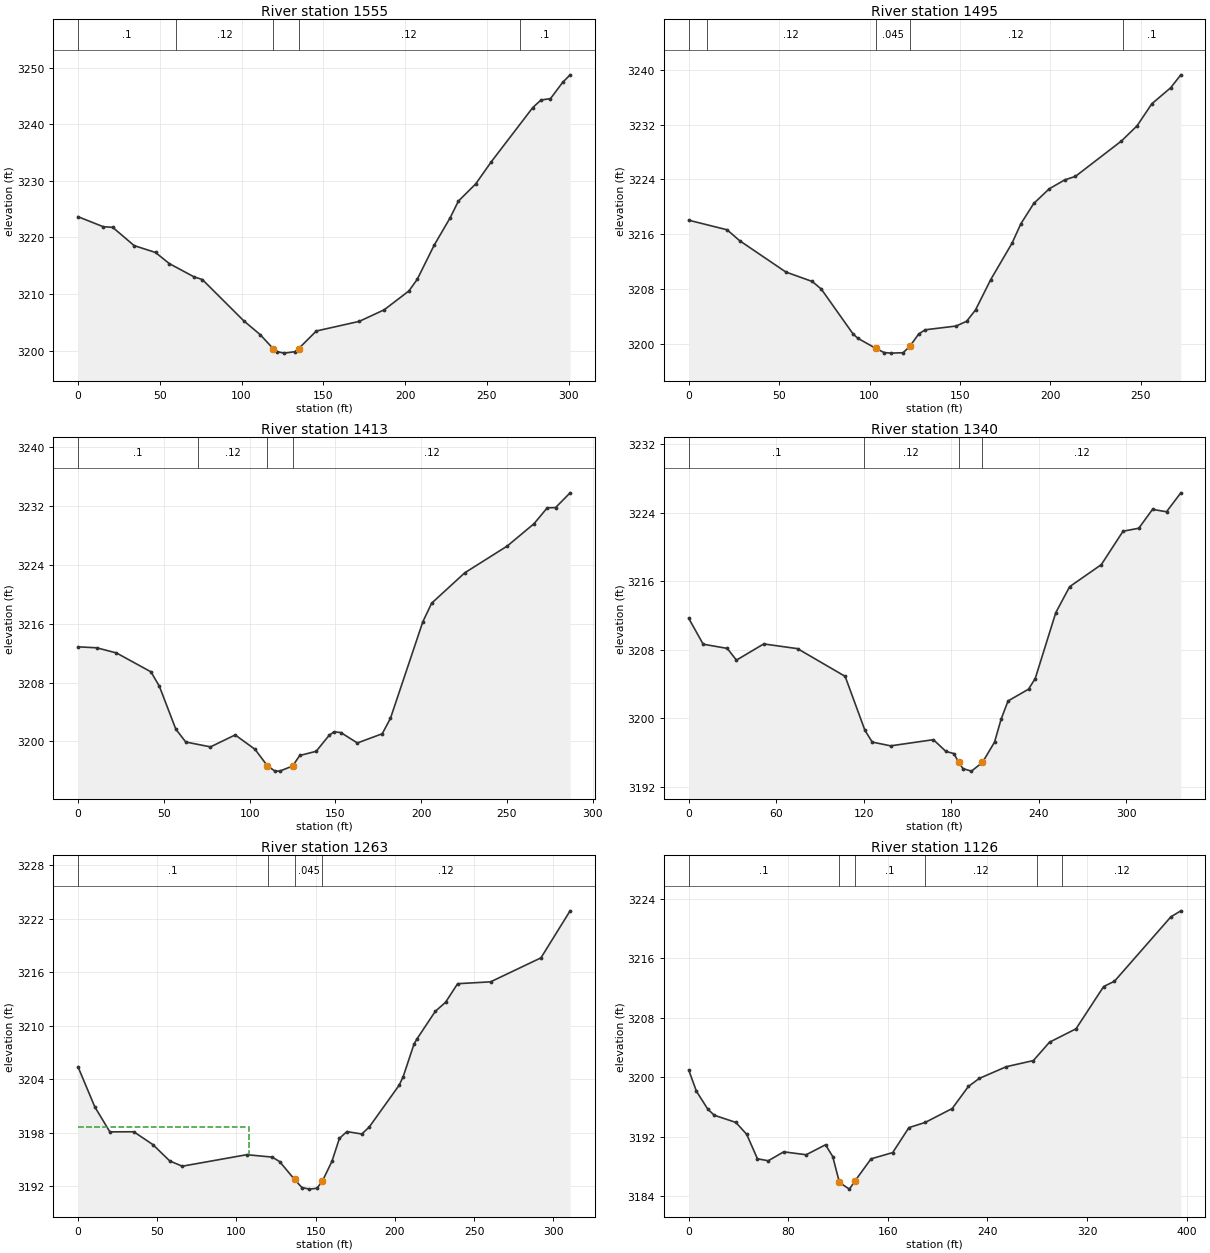
Type RM Length L Ch R = 1 ,1555    ,59.7,59.7,60
XS GIS Cut Line= 2
2347643.97047937730194.1382822682347882.26299783730010.380370024
#Sta/Elev= 30
       0 3223.67    15.4  3221.9    21.2 3221.79    34.3 3218.56    47.4 3217.34
    55.8 3215.38      71 3213.02      76 3212.56   101.3 3205.27   111.4 3202.81
  119.38 3200.32   121.5 3199.82     126 3199.54   132.6 3199.79   134.9 3200.33
   145.7 3203.45     172 3205.16   187.2  3207.2   202.3 3210.53   207.4 3212.58
   217.7 3218.59   227.6  3223.5   232.6 3226.43   243.2 3229.48   252.8 3233.42
   278.1 3242.98   283.1 3244.31   288.9 3244.55   296.3 3247.41   300.9 3248.76
#Mann= 5 ,-1,0
       0      .1       0      60     .12       0  119.38    .045       0
   134.9     .12       0     270      .1       0
Bank Sta=119.38,134.9
XS Rating Curve= 0 ,0
Exp/Cntr(USF)=0,0
Exp/Cntr=0.3,0.1

Type RM Length L Ch R = 1 ,1495    ,81.3,81.6,82.6
XS GIS Cut Line= 2
2347693.69763356730229.951386809 2347910.7216556730065.742945357
#Sta/Elev= 30
       0 3218.04    21.2 3216.64    28.2 3215.04    53.7 3210.47    68.3 3209.09
    73.3 3207.98    90.8 3201.45    93.4 3200.81   103.4 3199.32     108 3198.71
   111.8 3198.62   118.5 3198.68   122.2 3199.59   127.2 3201.43   130.8 3202.03
   147.9 3202.58   153.7 3203.28   158.6 3204.94     167 3209.37   178.7 3214.65
   183.7 3217.54   190.8 3220.49   199.3 3222.62   207.9 3223.93   213.8 3224.44
   239.3 3229.62   247.9 3231.83   256.1 3235.06   266.5 3237.39   272.1 3239.28
#Mann= 5 ,-1,0
       0      .1       0      10     .12       0   103.4    .045       0
   122.2     .12       0     240      .1       0
Bank Sta=103.4,122.2
XS Rating Curve= 0 ,0
Exp/Cntr(USF)=0,0
Exp/Cntr=0.3,0.1

Type RM Length L Ch R = 1 ,1413    ,73.3,73.7,74.3
XS GIS Cut Line= 2
2347728.80250401 730296.894169872347967.22674856730137.505586491
#Sta/Elev= 30
       0 3212.84    10.9 3212.71    22.4 3212.01    42.5 3209.45    47.4  3207.5
      57 3201.67    62.8 3199.93    77.2 3199.27    91.6 3200.89   103.2 3198.93
   110.43196.692   114.7    3196   117.6 3195.98  125.11 3196.68   129.2  3198.1
   138.8 3198.67   146.4 3200.85   149.3 3201.32   153.2 3201.21   162.8  3199.8
   177.3 3201.05   182.1 3203.15     201 3216.26   206.1 3218.76   225.4 3222.88
   250.2 3226.52   265.8 3229.55   273.5  3231.7   278.3 3231.72   286.8 3233.73
#Mann= 4 ,-1,0
       0      .1       0      70     .12       0   110.4    .045       0
  125.11     .12       0
Bank Sta=110.4,125.11
XS Rating Curve= 0 ,0
Exp/Cntr(USF)=0,0
Exp/Cntr=0.3,0.1

Type RM Length L Ch R = 1 ,1340    ,77.2,76.9,76.7
XS GIS Cut Line= 3
 2347708.0353824730386.6744247582347917.96168373730261.841378559
2347996.52918146730211.954516383
#Sta/Elev= 30
       0 3211.66     9.9 3208.64    26.4 3208.15    32.7 3206.78    51.4 3208.67
    74.6 3208.12   107.2 3204.89   120.8 3198.58   125.8 3197.22   138.4 3196.78
   167.7  3197.5   176.3 3196.13   181.7 3195.88   185.1 3194.87     188 3194.12
   193.8 3193.83  201.36 3194.85   209.6 3197.21   214.2 3199.93   218.9 3202.02
   232.9 3203.39   237.5 3204.63   251.6 3212.32   261.1 3215.35   282.8 3217.92
   297.7 3221.82   308.5 3222.17   317.9 3224.37   327.5 3224.09   337.3  3226.3
#Mann= 4 ,-1,0
       0      .1       0     120     .12       0   185.1    .045       0
  201.36     .12       0
Bank Sta=185.1,201.36
XS Rating Curve= 0 ,0
Exp/Cntr(USF)=0,0
Exp/Cntr=0.3,0.1

Type RM Length L Ch R = 1 ,1263    ,133.3,137.4,138.3
XS GIS Cut Line= 2
2347788.12549419730431.7976882582348051.79449106730267.641447165
#Sta/Elev= 30
       0 3205.41    10.6 3200.92    20.1 3198.12    35.2 3198.13    47.2  3196.7
    57.9 3194.86    65.8 3194.27   106.5 3195.56   122.6 3195.29   127.3 3194.78
   136.7 3192.78   141.3 3191.88   146.1  3191.7   150.8  3191.8   154.3 3192.62
   160.3 3194.83     165 3197.39   169.7 3198.15   179.1 3197.88   183.8 3198.66
   202.7 3203.35   205.2 3204.29   212.1 3207.97   213.9 3208.53   225.5 3211.63
     232 3212.65   239.6 3214.73   260.4 3214.94   292.2 3217.63   310.6  3222.9
#Mann= 4 ,-1,0
       0      .1       0     120     .12       0   136.7    .045       0
   154.3     .12       0
#XS Ineff= 2 , 0
          107.99 3198.63
Permanent Ineff=
       F       F
Bank Sta=136.7,154.3
XS Rating Curve= 0 ,0
Exp/Cntr(USF)=0,0
Exp/Cntr=0.3,0.1

Type RM Length L Ch R = 1 ,1126    ,58.5,58.9,59.5
XS GIS Cut Line= 2
2347809.32970196730534.4168531312348173.29885133730379.809155899
#Sta/Elev= 30
       0 3200.96     6.2 3198.11    15.3 3195.71    20.5 3194.89    37.9 3193.92
    46.6 3192.32    55.2 3189.04    63.9 3188.77    76.3 3189.97    94.4 3189.58
   109.9 3190.92   115.7 3189.34   121.13185.856   129.1 3184.96   133.5 3186.04
   146.5 3189.03   163.9 3189.87   176.9 3193.22     190 3193.92   211.7 3195.79
   224.7 3198.75   233.4 3199.83   255.2 3201.41   276.9 3202.23   289.9  3204.7
   311.2  3206.5   333.4 3212.18   342.1 3212.89   387.4 3221.54   395.4 3222.35
#Mann= 6 ,-1,0
       0      .1       0   121.1    .045       0   133.5      .1       0
     190     .12       0     280      .1       0     300     .12       0
Bank Sta=121.1,133.5
XS Rating Curve= 0 ,0
Exp/Cntr(USF)=0,0
Exp/Cntr=0.3,0.1

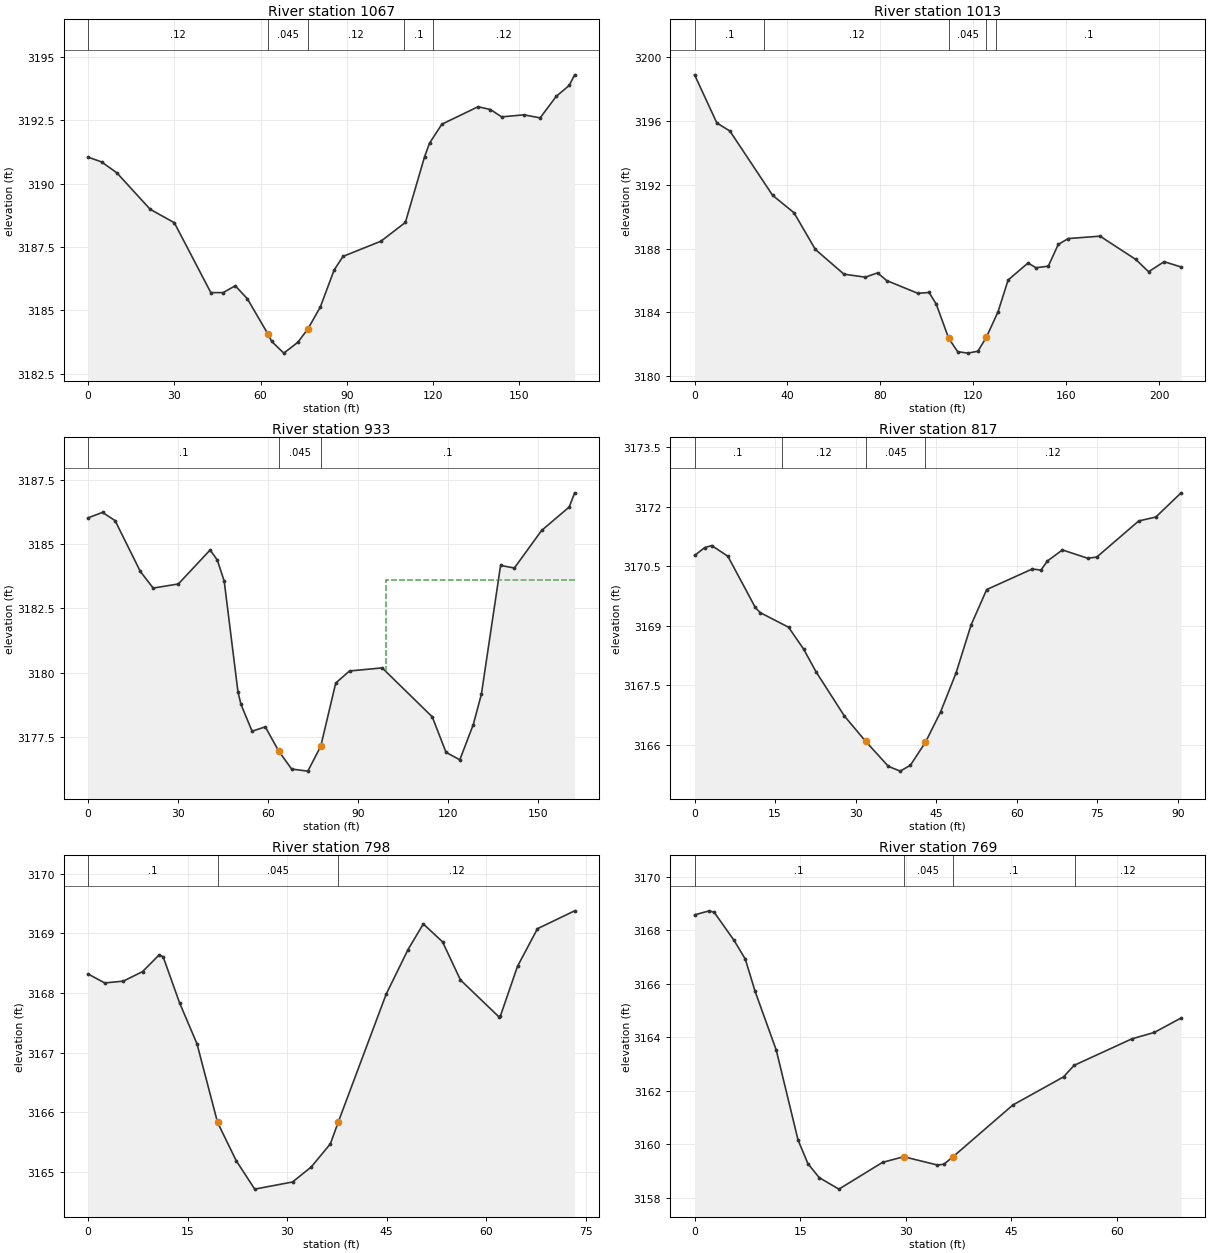
Type RM Length L Ch R = 1 ,1067    ,53.9,53.6,53.2
XS GIS Cut Line= 3
2347883.75734386730561.470588624 2348019.8463861730514.847490821
2348037.48755824730496.576276817
#Sta/Elev= 30
       0 3191.05     4.7 3190.86      10 3190.43    21.6 3188.99      30 3188.46
    42.7  3185.7      47  3185.7    51.2 3185.97    55.4 3185.46    62.6 3184.06
    63.9 3183.77    68.1 3183.31      73 3183.74    76.5 3184.27    80.8 3185.13
    85.6 3186.59    88.7 3187.13   101.9 3187.73   110.4 3188.47   117.1 3191.07
   118.8  3191.6   123.1 3192.35   135.7 3193.04     140 3192.93   143.9 3192.64
   151.7 3192.72   157.3  3192.6   162.9 3193.45   167.4 3193.88   169.3  3194.3
#Mann= 5 ,-1,0
       0     .12       0    62.6    .045       0    76.5     .12       0
     110      .1       0     120     .12       0
Bank Sta=62.6,76.5
XS Rating Curve= 0 ,0
Exp/Cntr(USF)=0,0
Exp/Cntr=0.3,0.1

Type RM Length L Ch R = 1 ,1013    ,85.1,80.2,75.7
XS GIS Cut Line= 2
2347863.27812327730632.1138049962348057.10384711 730552.62269297
#Sta/Elev= 30
       0 3198.89     9.6 3195.87    15.2 3195.37    33.6 3191.34    42.8 3190.25
      52 3187.95    64.3  3186.4    73.5 3186.21    78.8 3186.48    82.7    3186
    96.1  3185.2     101 3185.25   104.1 3184.51   109.43182.387   113.3 3181.54
   117.7 3181.45     122 3181.57   125.6 3182.43   130.7 3184.05     135 3186.03
   143.6  3187.1     147  3186.8   152.3  3186.9   156.6 3188.26   160.9 3188.63
   174.6 3188.78     190 3187.32   195.5 3186.55   202.2 3187.18   209.5 3186.85
#Mann= 5 ,-1,0
       0      .1       0      30     .12       0   109.4    .045       0
   125.6     .12       0     130      .1       0
Bank Sta=109.4,125.6
XS Rating Curve= 0 ,0
Exp/Cntr(USF)=0,0
Exp/Cntr=0.3,0.1

Type RM Length L Ch R = 1 ,933     ,114.4,115.3,116.1
XS GIS Cut Line= 4
2347963.58391887730693.9668885222347995.07964507730683.727186099
2348029.21507463730626.0640203112348059.12773287730571.586519893
#Sta/Elev= 30
       0 3186.02     4.8 3186.23       9 3185.91    17.4 3183.94    21.7 3183.29
    30.1 3183.45    40.7 3184.77    43.1 3184.38    45.4 3183.56      50 3179.25
      51 3178.77    54.7 3177.73    59.1  3177.9    63.63176.957    67.9 3176.26
    73.3 3176.18    77.63177.145    82.6  3179.6    87.2 3180.07    98.1 3180.19
   114.8 3178.29   119.4 3176.91     124 3176.62   128.5 3177.99   131.2 3179.17
   137.6 3184.17   142.2 3184.07   151.3 3185.53   160.5 3186.44   162.3 3186.99
#Mann= 3 ,-1,0
       0      .1       0    63.6    .045       0    77.6      .1       0
#XS Ineff= 2 , 0
                           99.51         3183.61
Permanent Ineff=
       F       F
Bank Sta=63.6,77.6
XS Rating Curve= 0 ,0
Exp/Cntr(USF)=0,0
Exp/Cntr=0.3,0.1

Type RM Length L Ch R = 1 ,817     ,18.5,19,20.4
XS GIS Cut Line= 4
2348093.17595304730730.7120884152348096.87813066730725.757070126
2348140.08226002730674.4979335942348151.21162053730661.141772195
#Sta/Elev= 28
       0 3170.77     1.9 3170.97     3.2 3171.02     6.2 3170.75    11.3 3169.46
    12.2 3169.33    17.5 3168.96    20.3 3168.41    22.6 3167.84    27.9 3166.72
   31.87 3166.08    36.1 3165.45    38.3 3165.33    40.2 3165.48      43 3166.06
    45.8 3166.82    48.7 3167.81    51.5 3169.02    54.4 3169.91    62.9 3170.43
    64.5  3170.4    65.7 3170.63    68.5 3170.91    73.2  3170.7    74.9 3170.73
    82.7 3171.64    85.9 3171.74    90.6 3172.35
#Mann= 4 ,-1,0
       0      .1       0   16.19     .12       0   31.87    .045       0
      43     .12       0
Bank Sta=31.87,43
XS Rating Curve= 0 ,0
Exp/Cntr(USF)=0,0
Exp/Cntr=0.3,0.1

Type RM Length L Ch R = 1 ,798     ,28.8,29.2,30.7
XS GIS Cut Line= 3
2348112.69231924730733.2501526352348146.37689467 730698.83330382
2348164.09610236730681.005611185
#Sta/Elev= 25
       0 3168.32     2.5 3168.17     5.3  3168.2     8.2 3168.36    10.7 3168.64
    11.3 3168.61    13.8 3167.83    16.4 3167.15    19.5 3165.83    22.3 3165.19
    25.1 3164.71    30.8 3164.83    33.6 3165.08    36.5 3165.47   37.67 3165.83
    44.9 3167.98    48.2 3168.73    50.5 3169.16    53.4 3168.86    56.1 3168.22
    61.9  3167.6    62.1 3167.61    64.7 3168.45    67.7 3169.08    73.3 3169.38
#Mann= 3 ,0,0
       0      .1       0    19.5    .045       0   37.67     .12       0
Bank Sta=19.5,37.67
XS Rating Curve= 0 ,0
Exp/Cntr(USF)=0,0
Exp/Cntr=0.3,0.1

Type RM Length L Ch R = 1 ,769     ,49.8,50.9,57
XS GIS Cut Line= 4
2348121.60465882730750.056278705 2348148.7647049730737.491690432
2348159.38266889730728.0941820682348177.19867295730710.512009501
#Sta/Elev= 22
       0 3168.57     2.1 3168.72     2.8 3168.66     5.6 3167.62     7.2 3166.92
     8.6 3165.71    11.6 3163.52    14.7 3160.16    16.1 3159.28    17.7 3158.76
    20.5 3158.33    26.7 3159.33    29.7 3159.54    34.5 3159.23    35.4 3159.26
   36.67 3159.53    45.2 3161.47    52.4 3162.52    53.9 3162.95    62.1 3163.94
    65.3 3164.18    69.1 3164.72
#Mann= 4 ,-1,0
       0      .1       0    29.7    .045       0   36.67      .1       0
    54.1     .12       0
Bank Sta=29.7,36.67
XS Rating Curve= 0 ,0
Exp/Cntr(USF)=0,0
Exp/Cntr=0.3,0.1