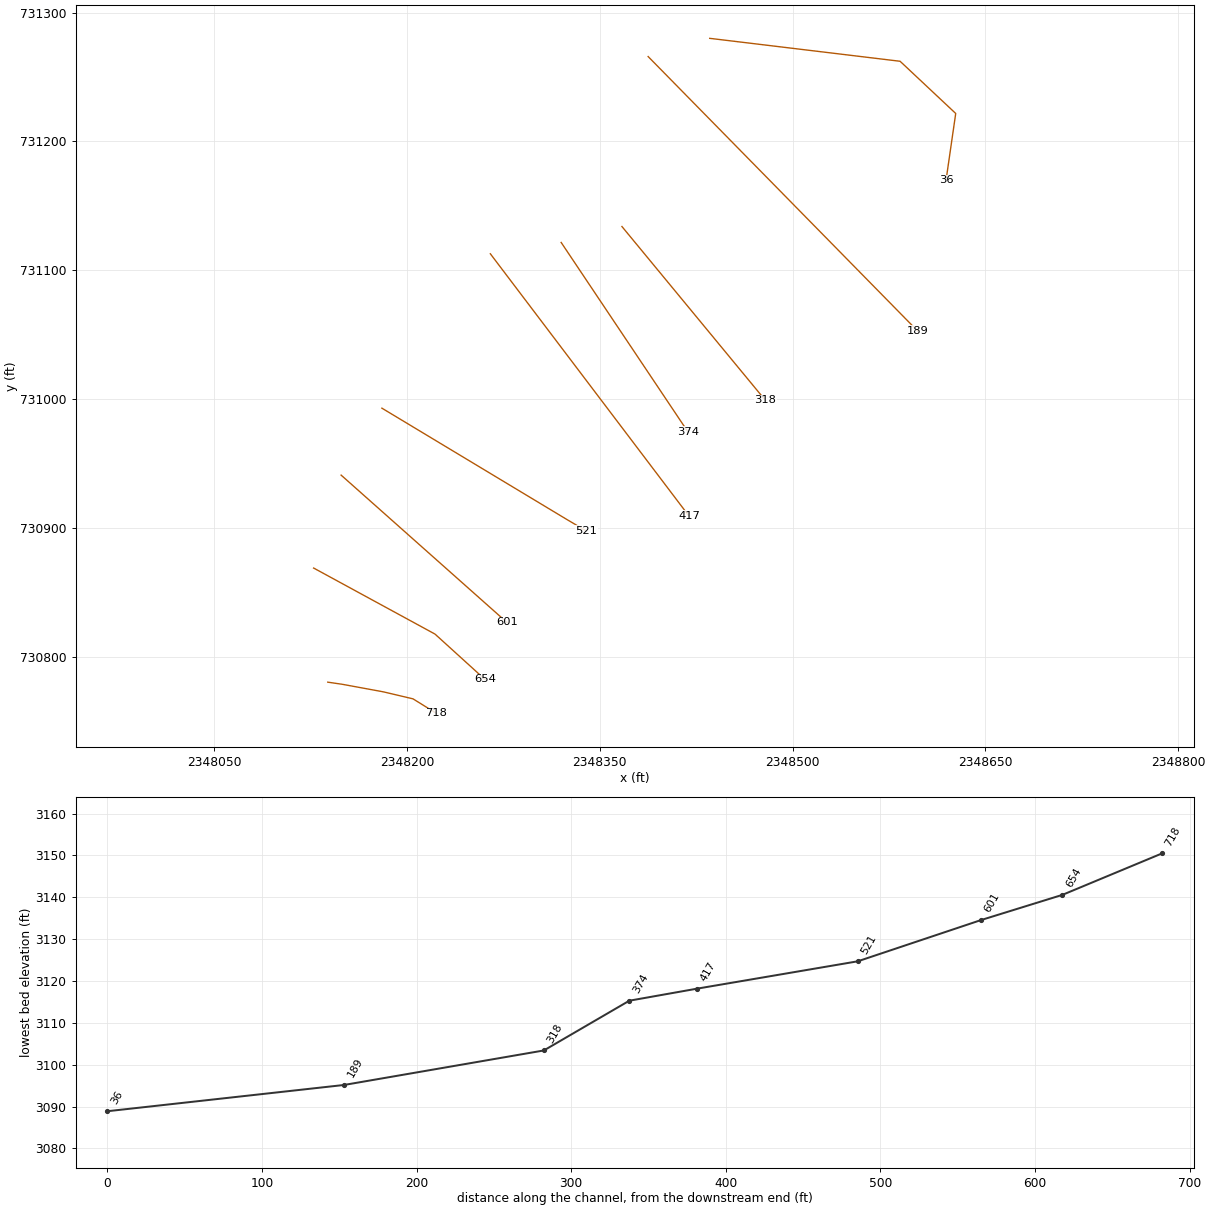
HEC-RAS study MOORERNT1.prj: MOORERNT1

--- MOORERNT1.g01 (geometry) --- (continued)

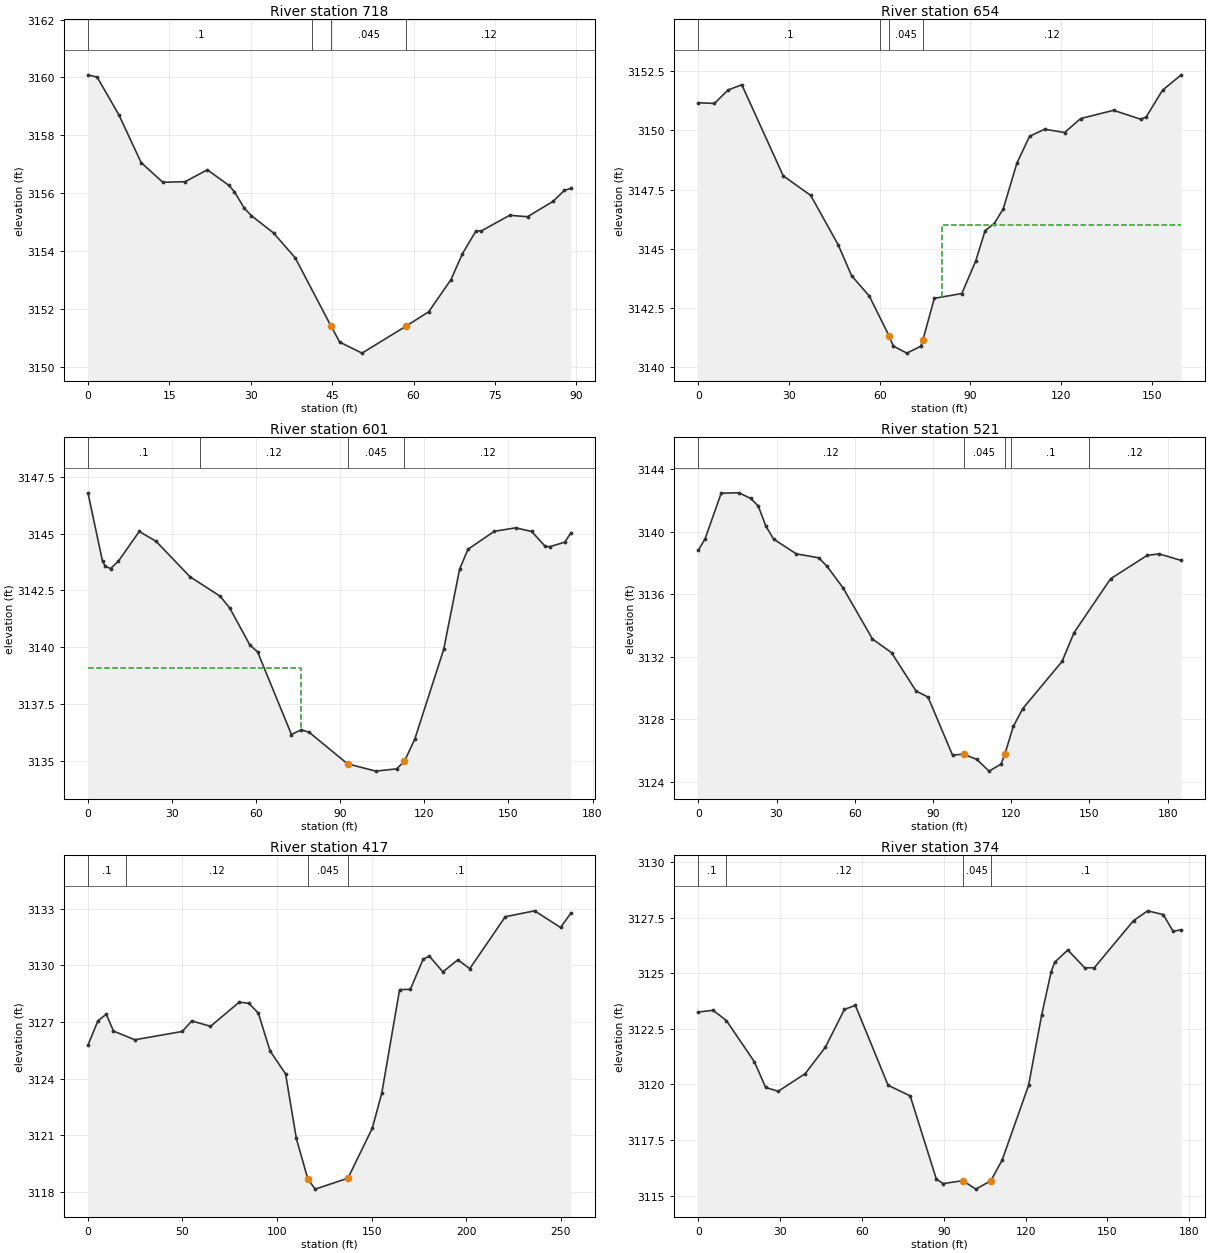
Type RM Length L Ch R = 1 ,718     ,67.2,64.4,65
XS GIS Cut Line= 5
2348138.50090998730780.720474485 2348149.7550814730779.076118197
2348181.66187099730773.2256583522348204.80328416 730767.78061996
2348223.03569397730756.514319102
#Sta/Elev= 27
       0 3160.09     1.7 3160.01     5.7 3158.71     9.8 3157.06    13.8 3156.38
    17.9  3156.4      22 3156.81      26 3156.27      27 3156.05    28.8 3155.49
    30.1 3155.23    34.2 3154.63    38.2 3153.77    44.8 3151.41    46.4 3150.86
    50.5 3150.48    58.7 3151.42    62.8 3151.91    66.9 3153.02      69 3153.91
    71.5  3154.7    72.5  3154.7    77.7 3155.24      81 3155.19    85.7 3155.72
    87.8  3156.1      89 3156.17
#Mann= 4 ,-1,0
       0      .1       0   41.37     .12       0    44.8    .045       0
    58.7     .12       0
Bank Sta=44.8,58.7
XS Rating Curve= 0 ,0
Exp/Cntr(USF)=0,0
Exp/Cntr=0.3,0.1

Type RM Length L Ch R = 1 ,654     ,54.2,52.7,52.7
XS GIS Cut Line= 3
2348127.50426782730869.2211935732348221.92634962730817.992191748
2348260.76663859730782.835033632
#Sta/Elev= 30
       0 3151.17     5.3 3151.14     9.9 3151.71    14.4 3151.93    28.1 3148.08
    37.2 3147.25    46.3 3145.16    50.7 3143.86    56.6 3142.99    63.2 3141.29
    64.5 3140.88      69 3140.58    73.6 3140.87    74.3 3141.13    78.1  3142.9
    87.2  3143.1    91.8 3144.48    94.9 3145.76    97.9 3146.06   100.9 3146.68
   105.4 3148.61   109.6 3149.75   114.6 3150.05   121.2 3149.91   126.5  3150.5
   137.4 3150.85   146.4 3150.47   148.2 3150.57   153.6  3151.7   159.8 3152.35
#Mann= 4 ,-1,0
       0      .1       0      60     .12       0    63.2    .045       0
    74.3     .12       0
#XS Ineff= 2 , 0
                           80.69         3145.99
Permanent Ineff=
       F       F
Bank Sta=63.2,74.3
XS Rating Curve= 0 ,0
Exp/Cntr(USF)=0,0
Exp/Cntr=0.3,0.1

Type RM Length L Ch R = 1 ,601     ,79,79.7,82.1
XS GIS Cut Line= 2
2348148.87497587730941.2871006432348277.88086063 730827.02953338
#Sta/Elev= 30
       0 3146.79     5.2 3143.78     6.2 3143.56     8.1 3143.46    10.9 3143.79
    18.3 3145.09    24.3 3144.66    36.4  3143.1    47.2 3142.24    50.6 3141.72
    57.8 3140.09    60.5  3139.8    72.6 3136.16    76.1 3136.37    78.9 3136.26
    92.63134.871   102.7 3134.55   110.1 3134.65   112.9 3134.98   116.6 3135.96
   126.9  3139.9   132.6 3143.44   135.6 3144.31     145  3145.1   152.6 3145.25
   158.3 3145.09   163.1 3144.44   164.7 3144.42   170.1 3144.62   172.3 3145.03
#Mann= 4 ,-1,0
       0      .1       0      40     .12       0    92.6    .045       0
   112.9     .12       0
#XS Ineff= 2 , 0
           75.84 3139.09
Permanent Ineff=
       F       F
Bank Sta=92.6,112.9
XS Rating Curve= 0 ,0
Exp/Cntr=0.3,0.1

Type RM Length L Ch R = 1 ,521     ,105.6,104,98.5
XS GIS Cut Line= 3
2348180.59488003730993.1950426222348324.63737253730906.769547122
2348339.49618087730898.055256529
#Sta/Elev= 30
       0 3138.81     2.6 3139.54     8.8 3142.46    15.6 3142.48    20.1 3142.12
      23 3141.64    25.9 3140.36    28.9 3139.52    37.6 3138.58    46.2 3138.33
    49.3  3137.8    55.5 3136.41    66.8 3133.14    74.1 3132.27    83.5 3129.82
    88.1 3129.43    97.5 3125.72   101.7 3125.79   106.8 3125.45   111.5  3124.7
   116.1 3125.15  117.54 3125.78   120.8 3127.56   124.4 3128.69   139.5 3131.71
   144.1 3133.55   158.1 3136.99   172.1 3138.48   176.7 3138.58   185.2 3138.16
#Mann= 5 ,-1,0
       0     .12       0   101.7    .045       0  117.54     .12       0
     120      .1       0     150     .12       0
Bank Sta=101.7,117.54
XS Rating Curve= 0 ,0
Exp/Cntr(USF)=0,0
Exp/Cntr=0.3,0.1

Type RM Length L Ch R = 1 ,417     ,44.1,43.7,43.2
XS GIS Cut Line= 2
2348264.95940657731112.9039698252348419.44810103730909.578522255
#Sta/Elev= 30
       0 3125.77     5.3 3127.07     9.7 3127.41    13.5 3126.52    24.8 3126.06
    49.9  3126.5    54.9 3127.06    64.8 3126.77      80 3128.05    85.1 3127.99
    90.1 3127.47    96.3 3125.47   104.5 3124.26   110.2 3120.84   116.3 3118.69
   120.2 3118.16   137.5 3118.74   150.4 3121.39   155.4 3123.25   164.8 3128.71
   170.5 3128.73   177.2 3130.31   180.5 3130.49   187.7 3129.65   195.6 3130.29
   201.9 3129.82   220.7 3132.57   236.2 3132.88   249.9    3132   255.4 3132.76
#Mann= 4 ,-1,0
       0      .1       0      20     .12       0   116.3    .045       0
   137.5      .1       0
Bank Sta=116.3,137.5
XS Rating Curve= 0 ,0
Exp/Cntr(USF)=0,0
Exp/Cntr=0.3,0.1

Type RM Length L Ch R = 1 ,374     ,54.6,55.3,56
XS GIS Cut Line= 2
2348320.04149611731121.6926158632348418.74805452730974.682848016
#Sta/Elev= 30
       0 3123.25     5.4 3123.33    10.3 3122.87    20.6 3121.01    24.7 3119.86
    29.3 3119.69    39.2 3120.48    46.6 3121.67    53.6 3123.37    57.6 3123.55
    69.6 3119.96    77.7 3119.48    87.3 3115.74    89.8 3115.54      97 3115.67
   101.8 3115.29  107.29 3115.67   111.4 3116.59   121.1 3119.95   125.9 3123.11
   129.4 3125.07   130.7 3125.49   135.5 3126.04   141.7 3125.24   145.2 3125.24
   159.6 3127.36   164.8  3127.8   170.5 3127.63   174.1 3126.88   177.1 3126.95
#Mann= 4 ,-1,0
       0      .1       0      10     .12       0      97    .045       0
  107.29      .1       0
Bank Sta=97,107.29
XS Rating Curve= 0 ,0
Exp/Cntr(USF)=0,0
Exp/Cntr=0.3,0.1

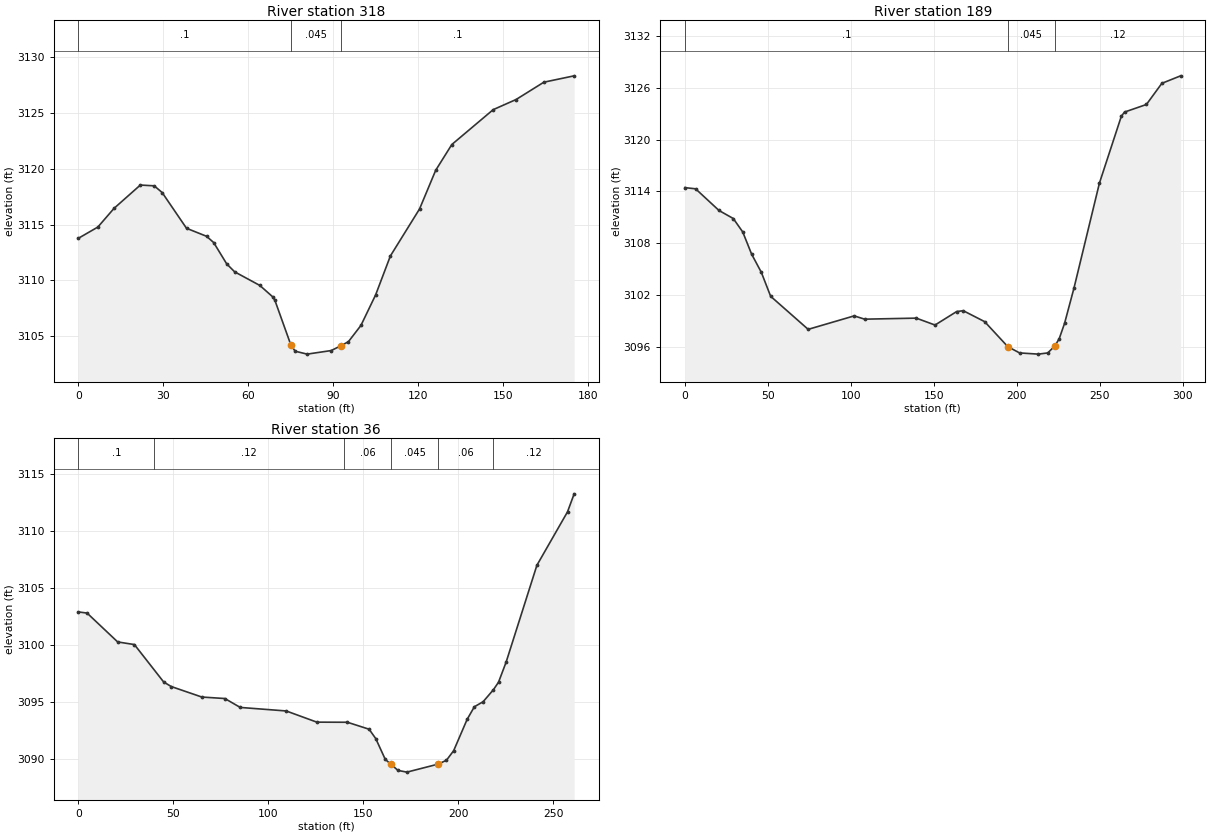
Type RM Length L Ch R = 1 ,318     ,122.1,129.3,129.2
XS GIS Cut Line= 2
2348367.31662956731134.0365908442348478.95205469 730999.18447599
#Sta/Elev= 30
       0 3113.77     6.9 3114.78    12.6 3116.45    21.9 3118.54    26.8 3118.47
    29.6 3117.87    38.2 3114.67    45.3 3113.95    47.8 3113.39    52.4 3111.48
    55.2 3110.77    64.1 3109.55    68.6 3108.54    69.4 3108.23    75.1 3104.19
    76.6 3103.66    80.8  3103.4    89.3 3103.72   92.89 3104.17    95.4 3104.52
    99.8 3105.97     105 3108.71   110.2 3112.19   120.5  3116.4   126.2 3119.86
   131.9 3122.17   146.5 3125.29   154.6  3126.2   164.4 3127.75   175.1 3128.32
#Mann= 3 ,0,0
       0      .1       0    75.1    .045       0   92.89      .1       0
Bank Sta=75.1,92.89
XS Rating Curve= 0 ,0
Exp/Cntr(USF)=0,0
Exp/Cntr=0.3,0.1

Type RM Length L Ch R = 1 ,189     ,147.6,153,150.2
XS GIS Cut Line= 2
2348387.69582119731265.8367886722348597.25991548731053.088057534
#Sta/Elev= 30
       0 3114.44     6.5  3114.3    20.6 3111.79    29.2 3110.86    34.9  3109.3
    40.2 3106.75    46.1 3104.62    51.7 3101.85    74.3 3098.02     102 3099.58
   108.3  3099.2   139.4 3099.32   150.7 3098.52   163.7 3100.08   167.7 3100.18
   180.6 3098.91   194.5 3096.02   201.6 3095.29   212.9 3095.15   218.6 3095.29
     223 3096.13   225.5 3096.95   228.7 3098.71   234.4 3102.82   249.7 3114.96
   262.9 3122.71   264.8 3123.19     278 3124.07   287.3 3126.52   298.6 3127.39
#Mann= 3 ,-1,0
       0      .1       0   194.5    .045       0     223     .12       0
Bank Sta=194.5,223
XS Rating Curve= 0 ,0
Exp/Cntr(USF)=0,0
Exp/Cntr=0.3,0.1

Type RM Length L Ch R = 1 ,36      ,,,
XS GIS Cut Line= 4
2348435.58948033731279.9695110562348583.67646697731262.186310422
2348626.93658476731221.7086934922348619.38302398731169.731188136
#Sta/Elev= 30
       0 3102.92     4.6 3102.82    20.7 3100.29    29.5 3100.06    44.9 3096.78
    48.9 3096.38      65 3095.46    77.1 3095.33    85.2 3094.55   109.4 3094.24
   125.5 3093.26   141.6 3093.25     153 3092.64   156.5 3091.82   161.5    3090
   164.4 3089.58   168.2 3089.03   172.9 3088.88   189.43089.585   193.7 3089.92
   197.5 3090.76   204.6 3093.51   208.4 3094.61     213 3095.05   218.4  3096.1
   221.1 3096.76   225.1 3098.52   241.3 3107.01   257.4 3111.69   260.9 3113.27
#Mann= 6 ,-1,0
       0      .1       0      40     .12       0     140     .06       0
   164.4    .045       0   189.4     .06       0   218.4     .12       0
Bank Sta=164.4,189.4
XS Rating Curve= 0 ,0
Exp/Cntr(USF)=0,0
Exp/Cntr=0.3,0.1
LCMann Table=0

Chan Stop Cuts=-1
Use User Specified Reach Order=0
Composite Channel Slope=5